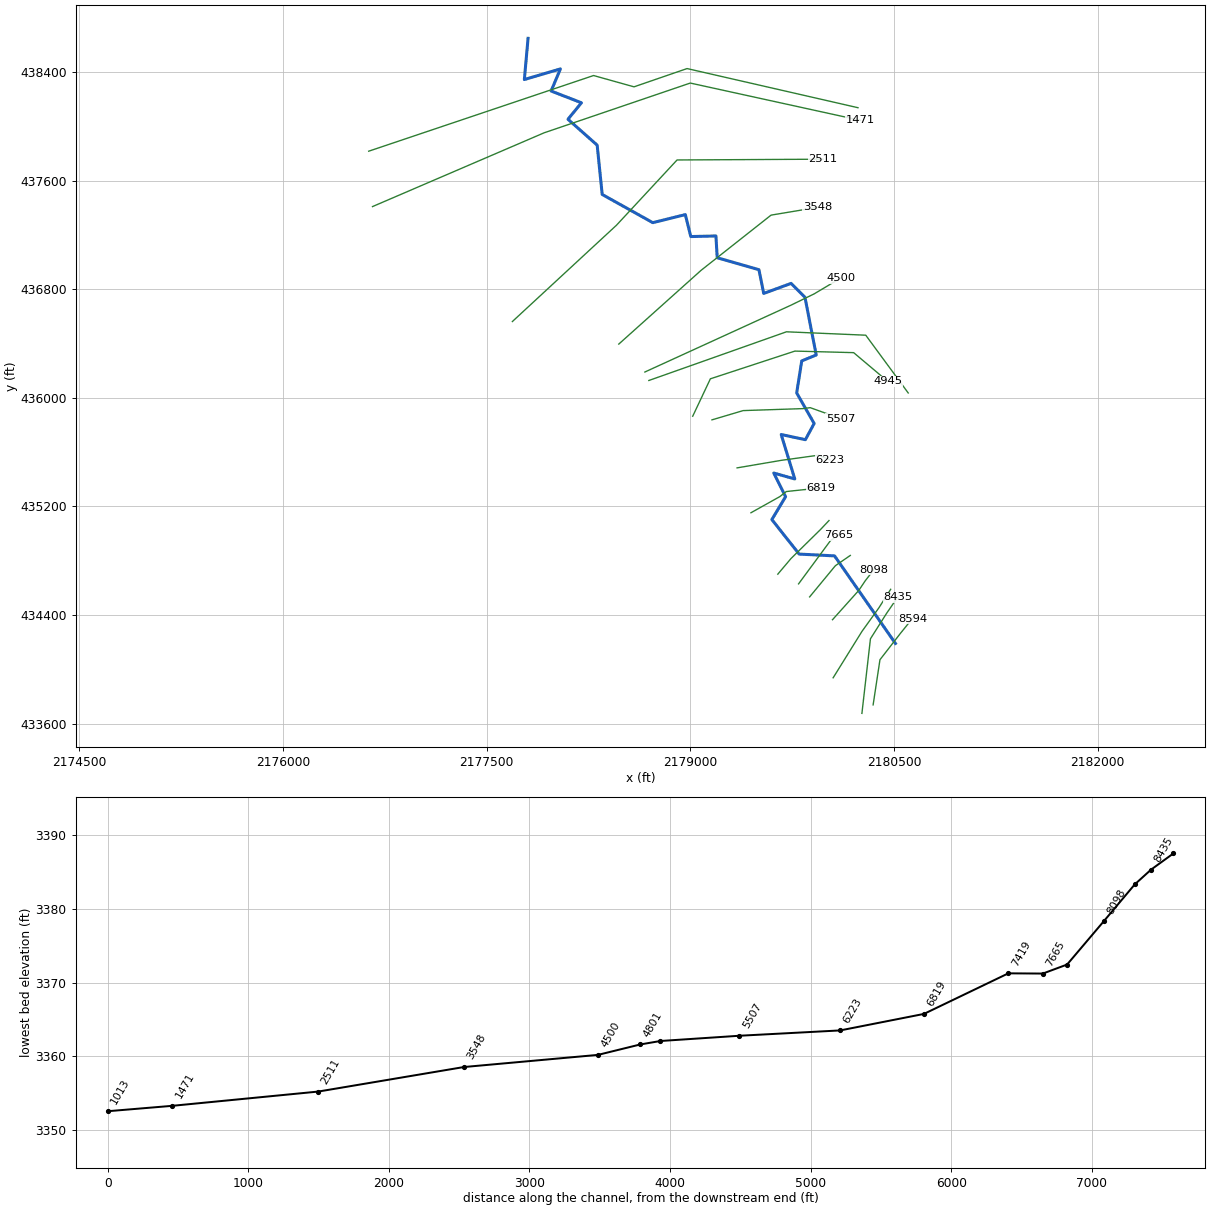
--- CHARLESCK.prj (project) ---

Proj Title=CHARLESCK
Current Plan=p01
Default Exp/Contr=0,0
English Units
Geom File=g01
Flow File=f01
Plan File=p01
Background Map Layer=Inundation Boundary (01pct Value_0)
BEGIN DESCRIPTION:
----------MODEL BY WOOD PLC 2021----------
Stream Name: Charles Creek
Flood Zone: Approximate
Pocahontas County, WV
HEC-RAS Version: RAS 6.1
Vertical Datum: NAVD88
Projection: NAD 1983 StatePlane West Virginia S FIPS 4702 (US Feet)
Terrain: 1-meter LIDAR (FEMA Region III 3DEP collected 2016-2018)
Land Use: 2019 NLCD
Hydrologic Method:
WV 2010 Regional Regression Equations
Model Notes:
Model snaps to Cranberry River / South Fork Cranberry River at the downstream
END DESCRIPTION:
DSS Export Rating Curves= 0
DSS Export Rating Curve Sorted= 0
DSS Export Volume Flow Curves= 0
DXF OffsetX= 0
DXF OffsetY= 0
DXF ScaleX= 0
DXF ScaleY= 0

--- CHARLESCK.p01 (plan) ---

Plan Title=Floodplain
Program Version=6.00
Short Identifier=Floodplain
Geom File=g01
Flow File=f01
Subcritical Flow
K Sum by GR= 0
Std Step Tol= 0.01
Critical Tol= 0.01
Num of Std Step Trials= 20
Max Error Tol= 0.3
Flow Tol Ratio= 0.001
Split Flow NTrial= 30
Split Flow Tol= 0.02
Split Flow Ratio= 0.02
Log Output Level= 0
Friction Slope Method= 1
Unsteady Friction Slope Method= 2
Unsteady Bridges Friction Slope Method= 1
Parabolic Critical Depth
Global Vel Dist= 0 , 0 , 0
Global Log Level= 0
CheckData=True
Encroach Param=-1 ,0,0, 0
Mapping Interval=1HOUR
Computation Time Step Use Courant=        0
Computation Time Step Use Time Series=    0
Computation Time Step Count To Double=0
Computation Time Step Max Doubling=0
Computation Time Step Max Halving=0
Computation Time Step Residence Courant=0
Run HTab= 0
Run UNet= 0
Run Sediment= 0
Run PostProcess= 0
Run WQNet= 0
Run RASMapper=-1
UNET Theta= 0
UNET Theta Warmup= 0
UNET ZTol= 0
UNET ZSATol= 0
UNET MxIter= 0
UNET Max Iter WO Improvement= 0
UNET MaxInSteps= 0
UNET DtIC= 0
UNET DtMin= 0
UNET MaxCRTS= 0
UNET WFStab= 0
UNET SFStab= 0
UNET WFX= 1
UNET SFX= 1
UNET Gravity=32.174
UNET 1D Methodology=Finite Difference
UNET DSS MLevel= 1
UNET Pardiso=0
UNET DZMax Abort= 0
UNET Use Existing IB Tables= 0
UNET Froude Reduction=False
UNET Froude Limit= 0
UNET Froude Power= 0
UNET D1 Cores= 0
UNET WindReference=Eulerian
UNET WindDragFormulation=Hsu (1988)
UNET D2 Coriolis=0
UNET D2 Cores= 0
UNET D2 Theta= 1
UNET D2 Theta Warmup= 1
UNET D2 Z Tol= 0.01
UNET D2 Volume Tol= 0.01
UNET D2 Max Iterations= 20
UNET D2 Equation= 0
UNET D2 RampUpFraction=0.1
UNET D2 TimeSlices= 1
UNET D2 Turbulence Formulation=Non-Conservative (original)
UNET D2 Eddy Viscosity=0.3
UNET D2 Transverse Eddy Viscosity=0.1
UNET D2 Smagorinsky Mixing=0
UNET D2 BCVolumeCheck=0
UNET D2 Cores=0
UNET D2 SolverType=PARDISO (Direct)
UNET D2 Minimum Iterations= 2147483647
UNET D2 Maximum Iterations= 2147483647
UNET D2 Restart Number= 10
UNET D2 Relaxation Coeff=1.3
UNET D2 SOR Precondition Iterations= 10
UNET D2 ILUT Maximum Fill= 8
UNET D2 ILUT Tolerance=1E-08
UNET D1D2 MaxIter= 0
UNET D1D2 ZTol=0.01
UNET D1D2 QTol=0.1
UNET D1D2 MinQTol=1
Write IC File= 0
Write IC File at Fixed DateTime=0
Write IC File at Sim End=0
Echo Input=False
Echo Parameters=False
Echo Output=False
Write Detailed= 0
HDF Write Warmup=0
HDF Write Time Slices=0
HDF Flush=0
HDF Compression= 1
HDF Chunk Size= 1
HDF Spatial Parts= 1
HDF Use Max Rows=0
HDF Fixed Rows= 1
Calibration Method= 0
Calibration Iterations= 20
Calibration Max Change=0.05
Calibration Tolerance=0.2
Calibration Maximum=1.5
Calibration Minimum=0.5
Calibration Optimization Method= 1
WQ AD Non Conservative
WQ ULTIMATE=-1
WQ Max Comp Step=1HOUR
WQ Output Interval=15MIN
WQ Output Selected Increments= 0
WQ Output face flow=0
WQ Output face velocity=0
WQ Output face area=0
WQ Output face dispersion=0
WQ Output cell volume=0
WQ Output cell surface area=0
WQ Output cell continuity=0
WQ Output cumulative cell continuity=0
WQ Output face conc=0
WQ Output face dconc_dx=0
WQ Output face courant=0
WQ Output face peclet=0
WQ Output face adv mass=0
WQ Output face disp mass=0
WQ Output cell mass=0
WQ Output cell source sink temp=0
WQ Output nsm pathways=0
WQ Output nsm derived pathways=0
WQ Create Restart=0
WQ Fixed Restart=0
WQ System Summary=0
WQ Write To DSS=0
Sorting and Armoring Iterations= 10
XS Update Threshold= 0.02
Bed Roughness Predictor= 0
Hydraulics Update Threshold= 0.02
Energy Slope Method= 1
Volume Change Method= 1
Sediment Retention Method= 0
Sediment TS Multiplier= 1
Warm Up Method= 0
XS Weighting Method= 0
Number of US Weighted Cross Sections= 1
Number of DS Weighted Cross Sections= 1
Upstream XS Weight=0
Main XS Weight=1
Downstream XS Weight=0
Number of DS XS's Weighted with US Boundary= 1
Upstream Boundary Weight= 1
Weight of XSs Associated with US Boundary= 0
Number of US XS's Weighted with DS Boundary= 1
Downstream Boundary Weight= 0.5
Weight of XSs Associated with DS Boundary= 0.5
Percentile Method= 0
Sediment Output Level= 3
Mass or Volume Output= 0
Output Increment Type= 1
Profile and TS Output Increment= 1
Transport Output Increment 1
XS Output Flag= 0
XS Output Increment= 10
Read HDF5 Sediment Hotstart= 0
Sediment Hotstart Type= 0
Write Gradation File= 0
Read Gradation Hotstart= 0
Write HDF5 File= 1
Write Binary Output= 1
Write DSS Sediment File= 0
DSS Sediment Output Type= 1
SV Curve= 0
Specific Gage Flag= 0
Subcell Erosion Methods= 0
Subcell Deposition Methods= 0
Advection Scheme= 1
Matrix Solver= 0
Implicit Weighting Factor= 1
Maximum Outer Loop Convergence Iterations= 5
Convergence Maximum Absolute= 0.001
Convergence RMSE= 0.0001
Grain Fractions Max Abs Error= 0.001
Max Subgrid Regions= 1
Max Subgrid Length Scale= 3.402823E+38
Initial Layer Thickness= 3.402823E+38
Min Layer Thickness= 3.402823E+38
Max Layer Thickness= 3.402823E+38
Number of Layers= 5

--- CHARLESCK.f01 (steady flow) ---

Flow Title=Flow
Program Version=6.00
Number of Profiles= 6
Profile Names=01pct,10pct,04pct,02pct,0_2pct,01plus
River Rch & RM=CHARLESCK,Main            ,8594
     468     245     328     396     656     692
River Rch & RM=CHARLESCK,Main            ,4500
     557     294     391     471     778     824
River Rch & RM=CHARLESCK,Main            ,3548
     647     344     456     549     902     957
River Rch & RM=CHARLESCK,Main            ,1471
     753     402     532     639    1050    1110
Boundary for River Rch & Prof#=CHARLESCK,Main            , 1
Up Type= 0
Dn Type= 3
Dn Slope=0.00178
Boundary for River Rch & Prof#=CHARLESCK,Main            , 2
Up Type= 0
Dn Type= 3
Dn Slope=0.00178
Boundary for River Rch & Prof#=CHARLESCK,Main            , 3
Up Type= 0
Dn Type= 3
Dn Slope=0.00178
Boundary for River Rch & Prof#=CHARLESCK,Main            , 4
Up Type= 0
Dn Type= 3
Dn Slope=0.00178
Boundary for River Rch & Prof#=CHARLESCK,Main            , 5
Up Type= 0
Dn Type= 3
Dn Slope=0.00178
Boundary for River Rch & Prof#=CHARLESCK,Main            , 6
Up Type= 0
Dn Type= 3
Dn Slope=0.00178
DSS Import GetInterval= 0
DSS Import GetPeak= 0
DSS Import FillOption= 0

--- CHARLESCK.g01 (geometry) ---

Geom Title=Geometry
Program Version=6.10

River Reach=CHARLESCK       ,Main
Reach XY= 30
     2180511.252      434191.2462180063.01856882434835.917914455
2179802.24202118434849.265788141     2179601.252       435103.33
     2179702.224      435271.607     2179614.964       435446.27
     2179770.014      435402.479     2179670.001      435729.788
     2179848.211      435691.744     2179912.728      435811.102
     2179784.064      436035.899     2179821.367      436271.973
     2179927.978      436315.518     2179845.024      436740.536
     2179743.081      436842.843     2179541.193      436768.842
     2179506.061      436943.604     2179198.937      437031.535
     2179189.304      437192.092     2179004.165      437187.651
      2178964.15      437349.221     2178724.357      437290.032
     2178351.726      437497.763     2178314.747      437860.907
     2178099.761      438051.481     2178198.891      438172.926
     2177975.419      438259.598     2178044.219      438422.404
     2177778.474      438344.098     2177805.773      438647.504

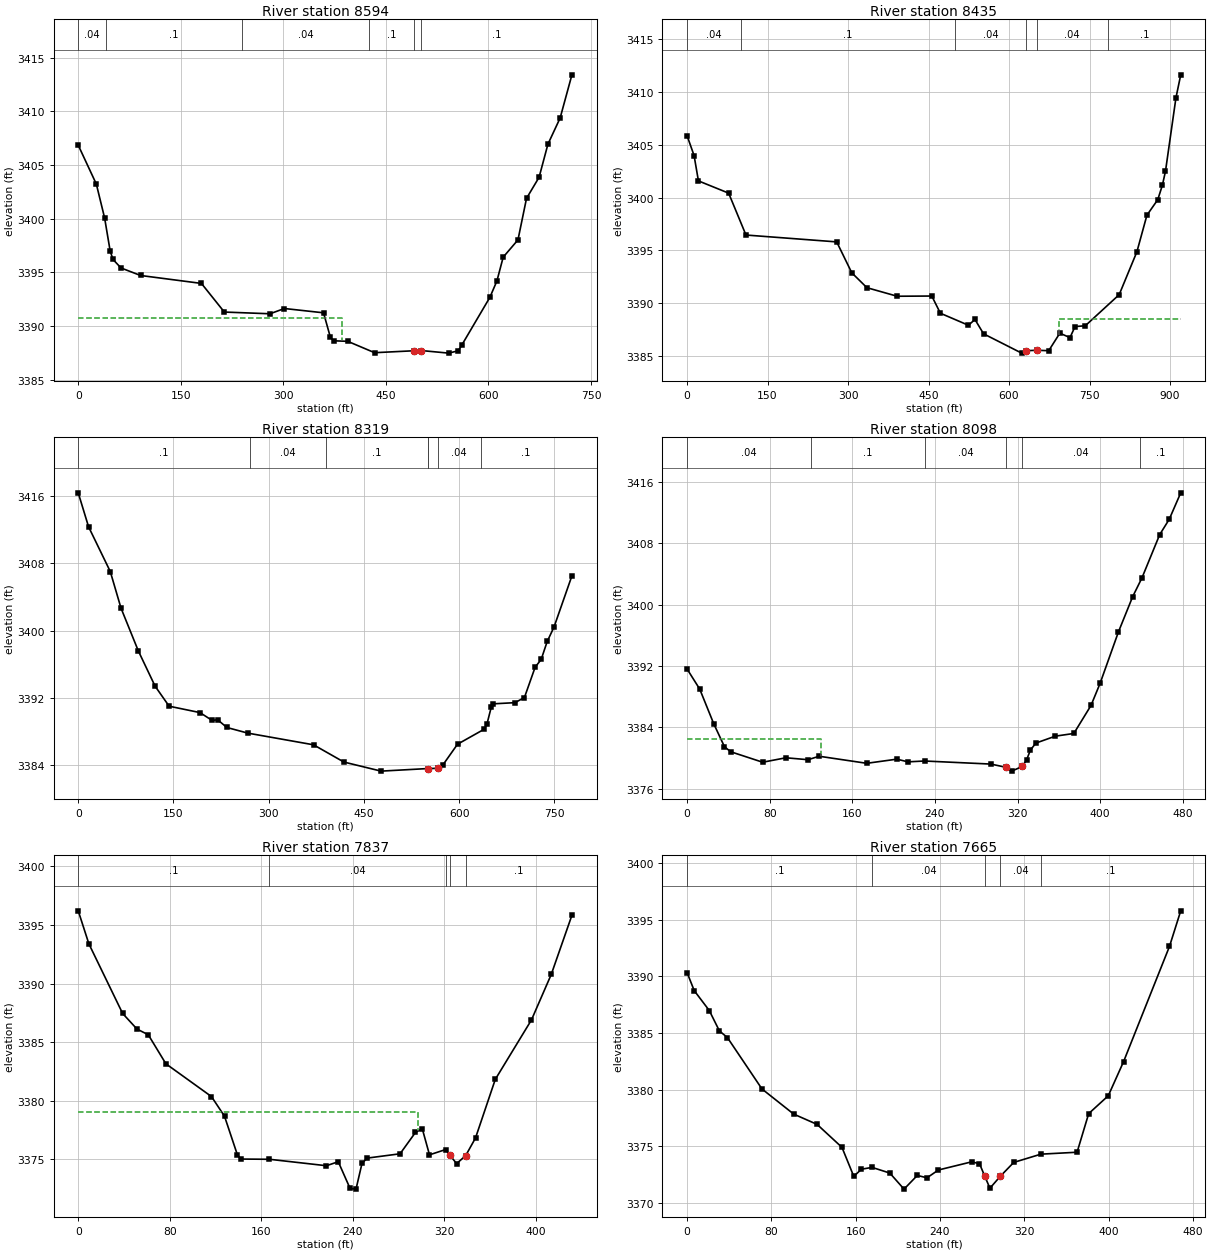
Type RM Length L Ch R = 1 ,8594    ,157.9,159,163.8
XS GIS Cut Line= 4
2180347.06625458433738.9743735972180397.33759363434071.124292364
2180546.35620584434263.2326237592180636.12645415 434374.54773167
#Sta/Elev= 30
       0 3406.85    26.5 3403.22    38.6 3400.06    46.7 3396.99    50.8  3396.2
    62.6  3395.4    91.2  3394.7   180.2 3393.96   213.7 3391.29   280.5 3391.13
   301.6 3391.62   358.8 3391.22   368.9 3388.92   373.6 3388.61   394.2 3388.56
   433.5  3387.5   490.7 3387.68   501.9  3387.7   541.8 3387.46   555.9 3387.68
   561.3 3388.24   602.1 3392.66   612.4 3394.19   621.6 3396.41   643.2 3398.02
   655.7 3401.89   674.1 3403.86     687 3406.94   704.9 3409.39   722.1 3413.41
#Mann= 6 ,-1,0
       0     .04       0      40      .1       0     240     .04       0
  425.93      .1       0   490.7    .045       0   501.9      .1       0
#XS Ineff= 2 , 0
          385.48 3390.73
Permanent Ineff=
       F       F
Bank Sta=490.7,501.9
XS Rating Curve= 0 ,0
Exp/Cntr(USF)=0,0
Exp/Cntr=0.3,0.1

Type RM Length L Ch R = 1 ,8435    ,80.2,115.6,98.7
XS GIS Cut Line= 4
2180264.47762613433676.1351997762180327.31679995434225.529119466
2180445.81352772434412.2512359622180528.40215617434532.543368705
#Sta/Elev= 30
       0 3405.88    13.1 3403.99    21.2 3401.59    77.5 3400.43   109.8 3396.46
   278.9 3395.81     307 3392.88   335.2 3391.47   391.6 3390.66   456.1 3390.68
   472.1 3389.05   524.4 3387.91   536.5 3388.46   552.6  3387.1   623.6 3385.27
   631.6  3385.5   651.6 3385.54     674  3385.5   694.7 3387.16   713.6 3386.74
   723.1 3387.79   742.1 3387.86   805.3 3390.81   838.3 3394.87     857 3398.34
   877.2 3399.81   885.8 3401.18   891.6 3402.51   911.1 3409.47     920 3411.64
#Mann= 6 ,-1,0
       0     .04       0     100      .1       0     500     .04       0
   631.6    .045       0   651.6     .04       0  784.12      .1       0
#XS Ineff= 2 , 0
                          693.07          3388.5
Permanent Ineff=
       F       F
Bank Sta=631.6,651.6
XS Rating Curve= 0 ,0
Exp/Cntr(USF)=0,0
Exp/Cntr=0.3,0.1

Type RM Length L Ch R = 1 ,8319    ,211.8,220.7,220.3
XS GIS Cut Line= 4
 2180052.6198401433938.2643248572180264.47762613434279.391268456
 2180388.3605688434451.7501452212180476.33541215434589.996327627
#Sta/Elev= 30
       0 3416.37    16.3 3412.33    50.5 3407.01    67.4 3402.66    94.7 3397.57
   121.1 3393.38   143.2    3391   191.8 3390.24   210.9 3389.31   219.6 3389.39
   234.1 3388.47   267.1  3387.8   370.7 3386.41   418.5 3384.36   477.1 3383.28
   551.7 3383.59   566.3 3383.61   574.6 3384.03   597.5 3386.48   639.2 3388.25
   643.7 3388.83   650.7  3390.9   653.4 3391.28     688 3391.42   702.9 3392.03
   719.8 3395.64   729.3 3396.56   738.8  3398.7   749.5 3400.41   777.7  3406.5
#Mann= 7 ,-1,0
       0      .1       0     270     .04       0     390      .1       0
  551.56     .04       0   551.7    .045       0   566.3     .04       0
  633.82      .1       0
Bank Sta=551.7,566.3
XS Rating Curve= 0 ,0
Exp/Cntr(USF)=0,0
Exp/Cntr=0.3,0.1

Type RM Length L Ch R = 1 ,8098    ,245.2,261.2,237.7
XS GIS Cut Line= 4
2180047.99136023434365.9682747832180241.47450553434581.720747363
 2180288.6191465 434652.051277332180351.99390977434733.974751798
#Sta/Elev= 30
       0 3391.61    12.3 3388.98    25.8 3384.48    36.2 3381.48    42.2 3380.82
    73.2 3379.45    95.7 3380.03   117.1 3379.78   127.9 3380.23     174 3379.31
   203.1 3379.85   213.9  3379.5     230 3379.61   294.2 3379.21309.06093378.783
   314.4 3378.29324.74093378.912   328.8 3379.77   332.5 3381.05   337.8 3381.95
   356.6 3382.85   374.5  3383.2   391.1 3386.85   399.9 3389.73   417.7 3396.45
   431.5 3401.05   440.5  3403.5   457.6 3409.12   466.9 3411.14     478 3414.58
#Mann= 6 ,-1,0
       0     .04       0     120      .1       0     230     .04       0
309.0609    .045       0324.7409     .04       0  438.51      .1       0
#XS Ineff= 2 , 0
          129.58 3382.54
Permanent Ineff=
       F       F
Bank Sta=309.0609,324.7409
XS Rating Curve= 0 ,0
Exp/Cntr(USF)=0,0
Exp/Cntr=0.3,0.1

Type RM Length L Ch R = 1 ,7837    ,133.2,172.6,158.2
XS GIS Cut Line= 3
2179879.50061547 434534.005202682180068.80596317  434763.3464072
2180179.02813689434839.463962148
#Sta/Elev= 30
       0 3396.21     9.3 3393.39    38.8 3387.44    51.3 3386.11    61.2 3385.62
    76.6 3383.14   116.4 3380.34   127.8 3378.66   139.1 3375.35     142    3375
   167.1 3374.98   216.8 3374.43   227.2 3374.77   237.5 3372.49   242.7 3372.43
   247.9 3374.62   252.4 3375.08   281.2 3375.45   294.6 3377.27   300.6 3377.59
   306.9 3375.36   320.9 3375.81  324.85 3375.31   330.6 3374.61   338.5 3375.29
   347.1  3376.8   364.4 3381.81     396 3386.89   413.3 3390.78431.3292 3395.83
#Mann= 5 ,-1,0
       0      .1       0   167.1     .04       0   320.9      .1       0
  324.85    .045       0   338.5      .1       0
#XS Ineff= 2 , 0
          296.62 3379.01
Permanent Ineff=
       F       F
Bank Sta=324.85,338.5
XS Rating Curve= 0 ,0
Exp/Cntr(USF)=0,0
Exp/Cntr=0.3,0.1

Type RM Length L Ch R = 1 ,7665    ,148.4,245.2,123.1
XS GIS Cut Line= 3
2179797.94609231434629.8935511212180032.72426504434948.203326361
 2180093.0251852434989.227722859
#Sta/Elev= 30
       0 3390.35     6.8 3388.75    21.1 3386.99    30.7 3385.19    38.3  3384.6
    71.1 3380.06   101.2 3377.84   123.4 3376.93     147  3374.9   158.2 3372.34
   165.5 3372.97   175.6 3373.13   192.4 3372.63   205.9 3371.21   218.5 3372.42
   227.7 3372.21   238.5  3372.9     270 3373.62   277.5 3373.46  282.52 3372.35
   287.4 3371.29   297.3 3372.35     310 3373.57   335.8  3374.3   370.1 3374.47
   381.1 3377.88   399.7 3379.46   414.2 3382.47   457.8 3392.66468.4602  3395.8
#Mann= 5 ,-1,0
       0      .1       0   175.6     .04       0  282.52    .045       0
   297.3     .04       0   335.8      .1       0
Bank Sta=282.52,297.3
XS Rating Curve= 0 ,0
Exp/Cntr(USF)=0,0
Exp/Cntr=0.3,0.1

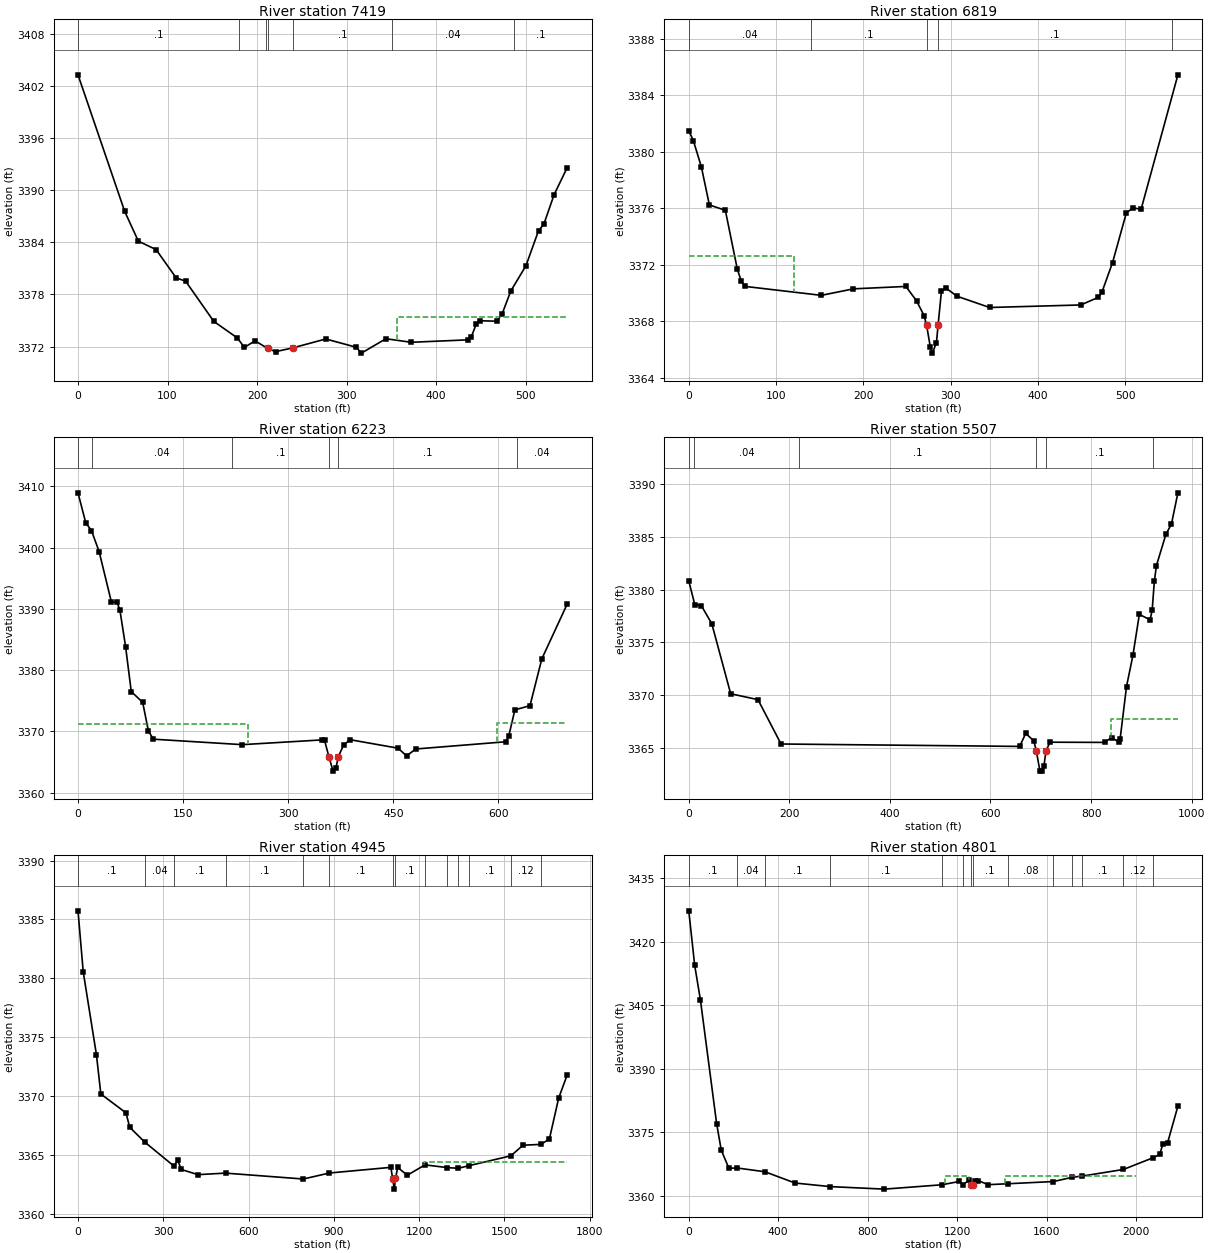
Type RM Length L Ch R = 1 ,7419    ,444.4,600.7,339.6
XS GIS Cut Line= 4
2179645.06291275434701.3114355382179742.01478093434816.217353382
2179961.05418682435031.6659493392180022.09795567435096.300528126
#Sta/Elev= 30
       0 3403.32    52.2 3387.57    67.4 3384.15    87.3 3383.17   109.7 3379.91
   120.2 3379.54   151.7  3374.9     178 3372.99   185.9  3371.9   197.8 3372.66
   211.9 3371.78   220.7 3371.41   240.2 3371.85   276.8 3372.87   310.9 3371.92
   316.6 3371.24   344.1  3372.9   372.2 3372.49   435.4 3372.77   439.5 3373.13
   445.1 3374.63   449.5 3374.97     468 3374.92   473.8 3375.74   483.5 3378.39
   500.5 3381.32   514.6 3385.37   520.4 3386.08     532 3389.52   546.5 3392.61
#Mann= 7 ,-1,0
       0      .1       0  180.34     .04       0  210.34      .1       0
   211.9    .045       0   240.2      .1       0  350.34     .04       0
  487.58      .1       0
#XS Ineff= 2 , 0
                          356.44         3375.36
Permanent Ineff=
       F       F
Bank Sta=211.9,240.2
XS Rating Curve= 0 ,0
Exp/Cntr(USF)=0,0
Exp/Cntr=0.3,0.1

Type RM Length L Ch R = 1 ,6819    ,301.1,595.5,252.3
XS GIS Cut Line= 4
2179447.56836645435153.7534870482179659.42615248435272.250214824
2179707.90208657435309.9537191172179962.84959179435336.884793611
#Sta/Elev= 30
       0  3381.5     5.3 3380.78    14.4 3378.94    23.6 3376.24    41.9 3375.86
    55.7 3371.67    60.3 3370.83    64.9 3370.47   151.9 3369.84   188.6  3370.3
   248.8 3370.47     261 3369.45   269.6 3368.41  272.583367.711   276.8 3366.17
   279.2 3365.75   283.8  3366.5  285.653367.715   289.5 3370.12   294.4 3370.37
   307.3 3369.78   344.7 3368.98   449.2 3369.16   469.3  3369.7   473.4 3370.06
   485.6 3372.16   501.5  3375.7   509.6 3376.03   518.3 3375.93   560.5 3385.45
#Mann= 5 ,-1,0
       0     .04       0     140      .1       0  272.58    .045       0
  285.65      .1       0  554.16     .04       0
#XS Ineff= 2 , 0
          120.79 3372.61
Permanent Ineff=
       F       F
Bank Sta=272.58,285.65
XS Rating Curve= 0 ,0
Exp/Cntr(USF)=0,0
Exp/Cntr=0.3,0.1

Type RM Length L Ch R = 1 ,6223    ,393.4,716.1,349.3
XS GIS Cut Line= 4
2179345.23028338435484.1080008492179671.99398724435539.765554804
2179944.89554212435577.4690590972180029.27957554435543.356364737
#Sta/Elev= 30
       0 3408.92    11.1 3404.01    19.2 3402.77    30.2 3399.31    47.6 3391.13
    55.7 3391.08    59.8 3389.79    67.9 3383.84      76  3376.5    92.3 3374.74
   100.4  3370.1   107.5 3368.73   234.3 3367.84   347.8 3368.61   351.8 3368.56
  358.013365.877     364 3363.52     368    3364   371.5 3365.88     379 3367.77
   388.2 3368.65   456.8 3367.26   468.9    3366   481.9 3367.13   610.5 3368.31
   614.8 3369.29   623.4 3373.51     645  3374.2   661.9 3381.84     698 3390.75
#Mann= 6 ,-1,0
       0      .1       0      20     .04       0     220      .1       0
  358.01    .045       0   371.5      .1       0  626.96     .04       0
#XS Ineff= 2 , 0
          242.57 3371.21  598.35         3371.44
Permanent Ineff=
       F       F
Bank Sta=358.01,371.5
XS Rating Curve= 0 ,0
Exp/Cntr(USF)=0,0
Exp/Cntr=0.3,0.1

Type RM Length L Ch R = 1 ,5507    ,346.3,562.4,451.9
XS GIS Cut Line= 5
2179160.30357185435837.8027792112179390.11540753435906.028167931
2179826.39881435435920.3914076612179883.85177327435927.573027527
2180108.27739406435846.779804043
#Sta/Elev= 30
       0 3380.82    11.9 3378.58    24.9 3378.48    45.8 3376.76    83.3 3370.13
   137.6 3369.57   183.5 3365.37     658 3365.14     670 3366.37   686.1 3365.67
  691.083364.708   698.2 3362.84   702.2  3362.8   706.3  3363.3  710.343364.707
   718.3 3365.54   826.9 3365.52   840.8 3365.98   855.1 3365.56   857.8 3365.85
   870.5 3370.81   883.2 3373.76     896 3377.64   917.3 3377.14   921.5 3378.02
   925.8 3380.77     930 3382.27   948.8 3385.23   959.8  3386.2   972.7 3389.16
#Mann= 6 ,-1,0
       0      .1       0      10     .04       0     220      .1       0
  691.08    .045       0  710.34      .1       0  924.15     .04       0
#XS Ineff= 2 , 0
                          839.38         3367.77
Permanent Ineff=
       F       F
Bank Sta=691.08,710.34
XS Rating Curve= 0 ,0
Exp/Cntr(USF)=0,0
Exp/Cntr=0.3,0.1

Type RM Length L Ch R = 1 ,4945    ,148.8,143.6,138.4
XS GIS Cut Line= 5
2179018.38654922  435864.51947592179148.51782735436140.091594288
2179771.10668741 436344.219089392180203.60181765 436332.73691779
  2180454.933796436120.954641622
#Sta/Elev= 30
       0 3385.73    18.4 3380.55    64.9  3373.5    80.4 3370.17   168.8 3368.57
   182.1 3367.34   235.2 3366.08   338.1 3364.04   350.7 3364.56   363.3 3363.76
   422.3 3363.32   519.1 3363.45   792.7 3362.95     885 3363.46  1101.1 3363.94
 1107.03 3362.99  1113.1 3362.09  1117.1    3363  1125.1 3363.93  1158.9 3363.27
    1221 3364.15  1299.2 3363.92  1338.2 3363.86  1377.2 3364.09  1523.3 3364.92
    1566 3365.82  1628.3 3365.89  1658.8 3366.34  1691.5 3369.831721.262 3371.77
#Mann= 14 ,-1,0
       0      .1       0   235.2     .04       0   338.1      .1       0
   519.1      .1       0   792.7     .08       0     885      .1       0
 1107.03    .045       0  1117.1      .1       0    1221     .08       0
  1299.2      .1       0  1338.2     .12       0  1377.2      .1       0
  1523.3     .12       0  1628.3     .04       0
#XS Ineff= 2 , 0
                         1219.29         3364.41
Permanent Ineff=
       F       F
Bank Sta=1107.03,1117.1
XS Rating Curve= 0 ,0
Exp/Cntr(USF)=0,0
Exp/Cntr=0.3,0.1

Type RM Length L Ch R = 1 ,4801    ,138.4,301,287.3
XS GIS Cut Line= 4
2178695.27272027436127.5982159692179708.78407881436486.289478662
2180292.70008784436461.2645068462180605.51223554436035.839985978
#Sta/Elev= 30
       0 3427.29    26.4 3414.45    52.1 3406.26   124.6 3377.07   145.2 3370.83
   179.2 3366.56   217.4  3366.6   340.4 3365.72   475.2 3363.06  632.043362.217
     875 3361.62  1130.6 3362.64  1210.6 3363.43  1225.3 3362.68  1254.7 3363.72
  1261.5 3362.51 1269.48  3362.5  1278.7 3363.59  1294.7 3363.63  1338.7 3362.67
  1426.8 3362.89    1631 3363.41  1714.3 3364.41    1760  3364.7  1943.8 3366.26
  2076.7 3369.03  2106.5 3369.82  2119.9 3372.22  2141.3 3372.53  2187.6 3381.21
#Mann= 14 ,-1,0
       0      .1       0   217.4     .04       0   340.4      .1       0
  632.04      .1       0  1130.6     .08       0  1225.3      .1       0
  1261.5    .045       0 1269.48      .1       0  1426.8     .08       0
    1631      .1       0  1714.3     .12       0    1760      .1       0
  1943.8     .12       0  2076.7     .04       0
#XS Ineff= 2 ,-1
  1146.6  1254.7  3364.6 1415.53    2000  3364.6
Permanent Ineff=
       F       F
Bank Sta=1261.5,1269.48
XS Rating Curve= 0 ,0
Exp/Cntr(USF)=0,0
Exp/Cntr=0.3,0.1

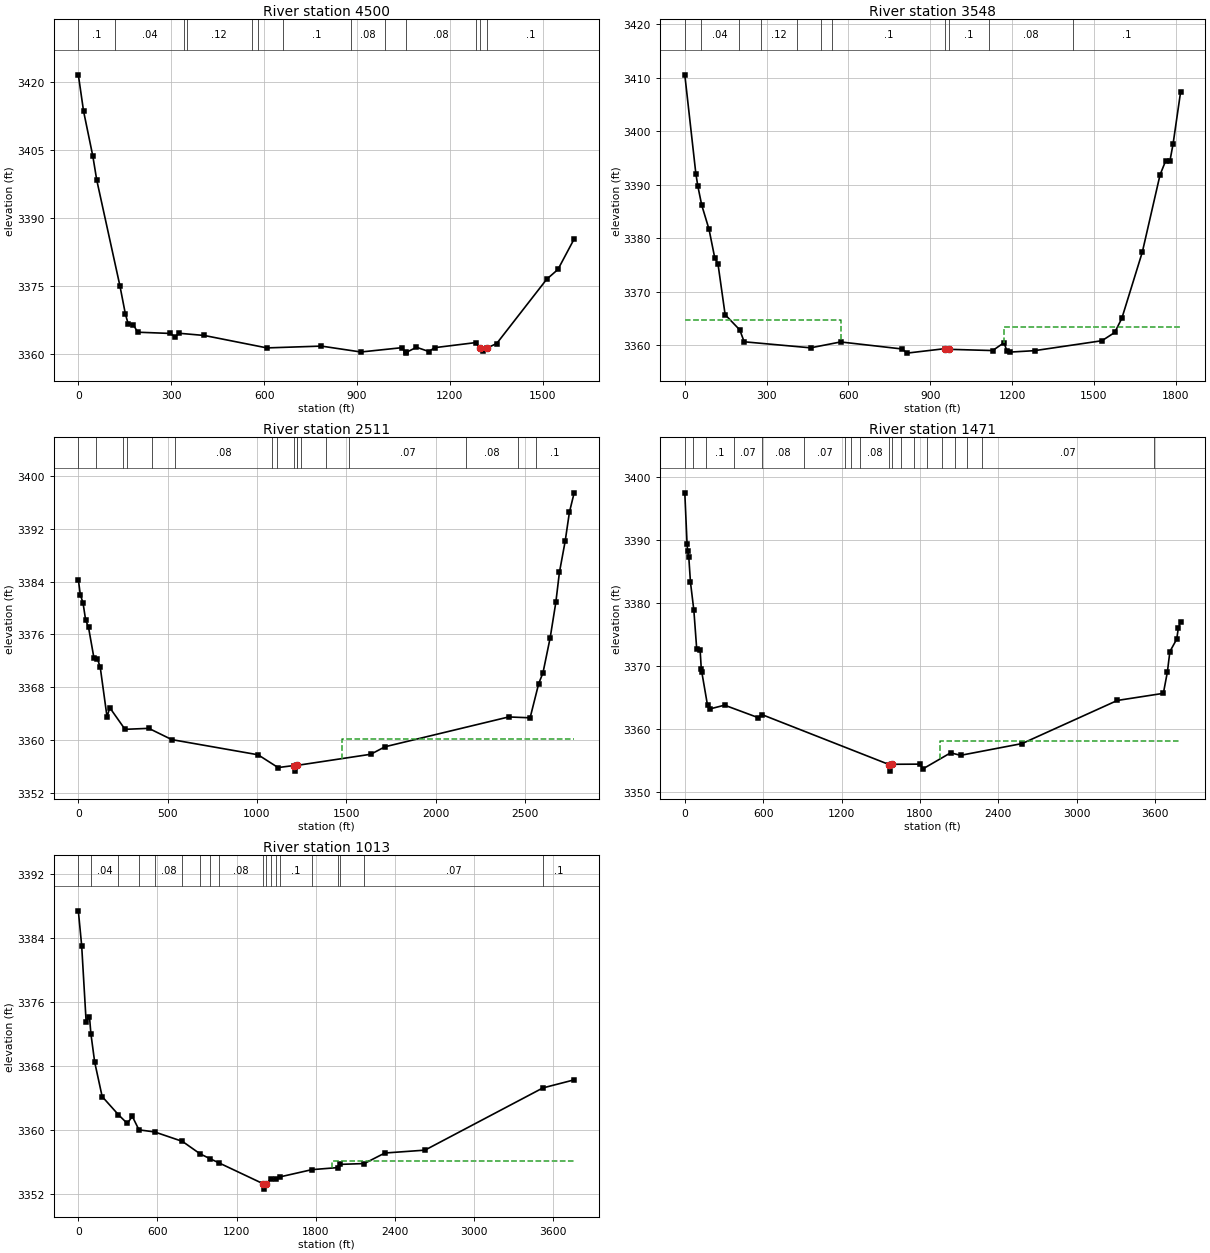
Type RM Length L Ch R = 1 ,4500    ,523.8,952.5,669.2
XS GIS Cut Line= 4
2178666.07691982436190.1606455092179742.15070789436682.318424552
2179913.15468197436765.7349972712180109.18362786436882.518199078
#Sta/Elev= 30
       0 3421.54    16.9 3413.53    46.8 3403.63    59.5 3398.34   134.3 3375.05
   152.1 3368.79   160.8 3366.73   178.2 3366.44   191.4 3364.82     297 3364.55
   311.7 3363.81   326.8 3364.58     407  3364.1   609.3 3361.36   785.2 3361.76
   912.8 3360.46  1045.1 3361.41    1058 3360.21    1060 3360.39  1092.4  3361.5
  1132.5 3360.56  1150.7 3361.41  1283.4 3362.53  1296.8 3361.37  1305.7 3360.59
 1321.543361.383  1351.5 3362.33  1513.1  3376.5  1549.3 3378.65  1601.7 3385.37
#Mann= 13 ,-1,0
       0      .1       0     120     .04       0     340      .1       0
     350     .12       0     560      .1       0     580     .12       0
     660      .1       0     880     .08       0     990      .1       0
    1060     .08       0 1283.28      .1       0  1296.8    .045       0
 1321.54      .1       0
Bank Sta=1296.8,1321.54
XS Rating Curve= 0 ,0
Exp/Cntr(USF)=0,0
Exp/Cntr=0.3,0.1

Type RM Length L Ch R = 1 ,3548    ,681.8,1036.7,749.7
XS GIS Cut Line= 4
2178474.02427832436395.8013775562179080.48221441436939.324999525
2179595.39932996437345.537390682  2179938.677407437402.750403521
#Sta/Elev= 30
       0 3410.59    40.5 3392.13    47.8 3389.79      62 3386.25    88.8 3381.72
   110.1 3376.31   121.5 3375.32   147.9 3365.76   201.6 3362.91   217.7 3360.69
   461.4 3359.56   571.4 3360.66   797.8 3359.34   814.4 3358.57     953  3359.4
   970.3 3359.28  1128.8 3359.05  1170.6 3360.52  1180.8 3359.03  1191.4 3358.76
  1282.4 3359.03  1529.7 3360.89  1576.5 3362.43  1602.7 3365.09  1677.8 3377.47
  1742.7 3391.89    1763 3394.47  1779.2 3394.55  1790.4 3397.64  1818.2 3407.41
#Mann= 11 ,-1,0
       0      .1       0      60     .04       0     200      .1       0
     280     .12       0     410      .1       0     500     .08       0
     540      .1       0     953    .045       0   970.3      .1       0
 1114.38     .08       0 1424.38      .1       0
#XS Ineff= 2 , 0
          574.26 3364.74 1170.52         3363.47
Permanent Ineff=
       F       F
Bank Sta=953,970.3
XS Rating Curve= 0 ,0
Exp/Cntr(USF)=0,0
Exp/Cntr=0.3,0.1

Type RM Length L Ch R = 1 ,2511    ,861.9,1039.5,674.9
XS GIS Cut Line= 4
2177690.20600243436561.7191147882178456.86037447437271.160473991
2178903.12187461437751.7497818382179978.72651598437757.471083122
#Sta/Elev= 30
       0 3384.32      11 3382.04    26.5 3380.74    40.8 3378.19    57.2 3377.04
    87.5  3372.4   106.2 3372.33   122.6 3371.02   160.7 3363.47   175.9 3364.88
   261.4 3361.59   394.5 3361.74   523.4 3360.03  1006.3 3357.73  1118.3 3355.79
  1206.8  3356.1  1215.3 3355.25 1224.35 3356.12  1637.3 3357.81  1717.4 3358.95
  2409.4 3363.47  2529.4 3363.34  2577.4 3368.52  2601.4 3370.17  2641.9 3375.51
  2673.4 3380.85  2693.4 3385.39  2725.5  3390.1  2749.4 3394.52    2776 3397.47
#Mann= 17 ,-1,0
       0      .1       0     100     .04       0     250     .12       0
     270     .08       0     410     .12       0     540     .08       0
 1084.54      .1       0 1114.54     .08       0  1206.8    .045       0
 1224.35     .08       0 1224.54      .1       0 1244.54     .08       0
 1384.54      .1       0 1514.54     .07       0 2170.37     .08       0
 2460.37     .07       0 2560.37      .1       0
#XS Ineff= 2 , 0
                         1475.25         3360.08
Permanent Ineff=
       F       F
Bank Sta=1206.8,1224.35
XS Rating Curve= 0 ,0
Exp/Cntr(USF)=0,0
Exp/Cntr=0.3,0.1

Type RM Length L Ch R = 1 ,1471    ,292.6,458.6,287.1
XS GIS Cut Line= 4
2176660.37177133437408.4717048052177924.77935507437951.995326774
2179000.38399644438318.1586089442180253.34897761438043.536147317
#Sta/Elev= 30
       0 3397.54    17.2 3389.48    21.6 3388.27    30.3 3387.41    43.3 3383.35
    69.4 3378.85    91.2 3372.72   117.3 3372.56     126 3369.61   130.4 3369.03
   173.9 3363.78   191.4  3363.2   304.6  3363.8   561.4 3361.82   591.9 3362.29
  1565.8 3354.35  1574.2 3353.32  1587.9 3354.41    1802 3354.43  1821.2 3353.66
  2034.8 3356.23  2110.9 3355.83  2581.9  3357.7  3310.8 3364.55    3663 3365.68
  3694.1  3369.1  3712.8 3372.31  3765.3 3374.29  3777.6 3376.043795.209 3377.07
#Mann= 19 ,-1,0
       0      .1       0      60     .04       0     160      .1       0
     380     .07       0     590     .08       0     910     .07       0
    1230     .08       0    1270     .07       0    1340     .08       0
  1565.8    .045       0  1587.9     .08       0 1656.28      .1       0
 1756.28     .08       0 1856.28      .1       0 1966.28     .08       0
 2066.28     .07       0 2156.28     .08       0 2276.28     .07       0
  3592.5      .1       0
#XS Ineff= 2 , 0
                          1953.8         3358.11
Permanent Ineff=
       F       F
Bank Sta=1565.8,1587.9
XS Rating Curve= 0 ,0
Exp/Cntr(USF)=0,0
Exp/Cntr=0.3,0.1

Type RM Length L Ch R = 1 ,1013    ,,,
XS GIS Cut Line= 5
 2176632.1795659437816.2871360342178288.14688623438373.614628756
  2178586.028822438290.3358080042178976.79867322438424.863133834
2180235.59007919438136.590292771
#Sta/Elev= 30
       0 3387.43    25.3 3383.08    59.1 3373.56    84.4  3374.2    95.4 3372.03
   123.9  3368.5   180.7 3364.18   303.8 3361.91   371.4 3360.81   409.4  3361.7
     460 3360.01   578.6 3359.75   789.2 3358.57   924.3    3357  1000.2 3356.39
  1063.6  3355.9  1401.2 3353.27  1409.6 3352.59 1425.62 3353.26  1459.6 3353.84
  1497.5 3353.86    1532 3354.13  1772.2 3355.03  1971.7 3355.29  1987.8 3355.69
  2168.8 3355.79  2324.8 3357.11  2629.2 3357.47  3524.1 3365.263761.198 3366.27
#Mann= 19 ,-1,0
       0      .1       0    95.4     .04       0   303.8      .1       0
     460     .07       0   578.6     .08       0   789.2     .07       0
   924.3     .08       0  1000.2     .07       0  1063.6     .08       0
  1401.2    .045       0 1425.62     .08       0  1459.6      .1       0
  1497.5     .08       0    1532      .1       0  1772.2     .08       0
  1971.7     .07       0  1987.8     .08       0  2168.8     .07       0
  3524.1      .1       0
#XS Ineff= 2 , 0
                         1927.11         3356.11
Permanent Ineff=
       F       F
Bank Sta=1401.2,1425.62
XS Rating Curve= 0 ,0
Exp/Cntr(USF)=0,0
Exp/Cntr=0.3,0.1
LCMann Table=0

Chan Stop Cuts=-1
Use User Specified Reach Order=0
Composite Channel Slope=5